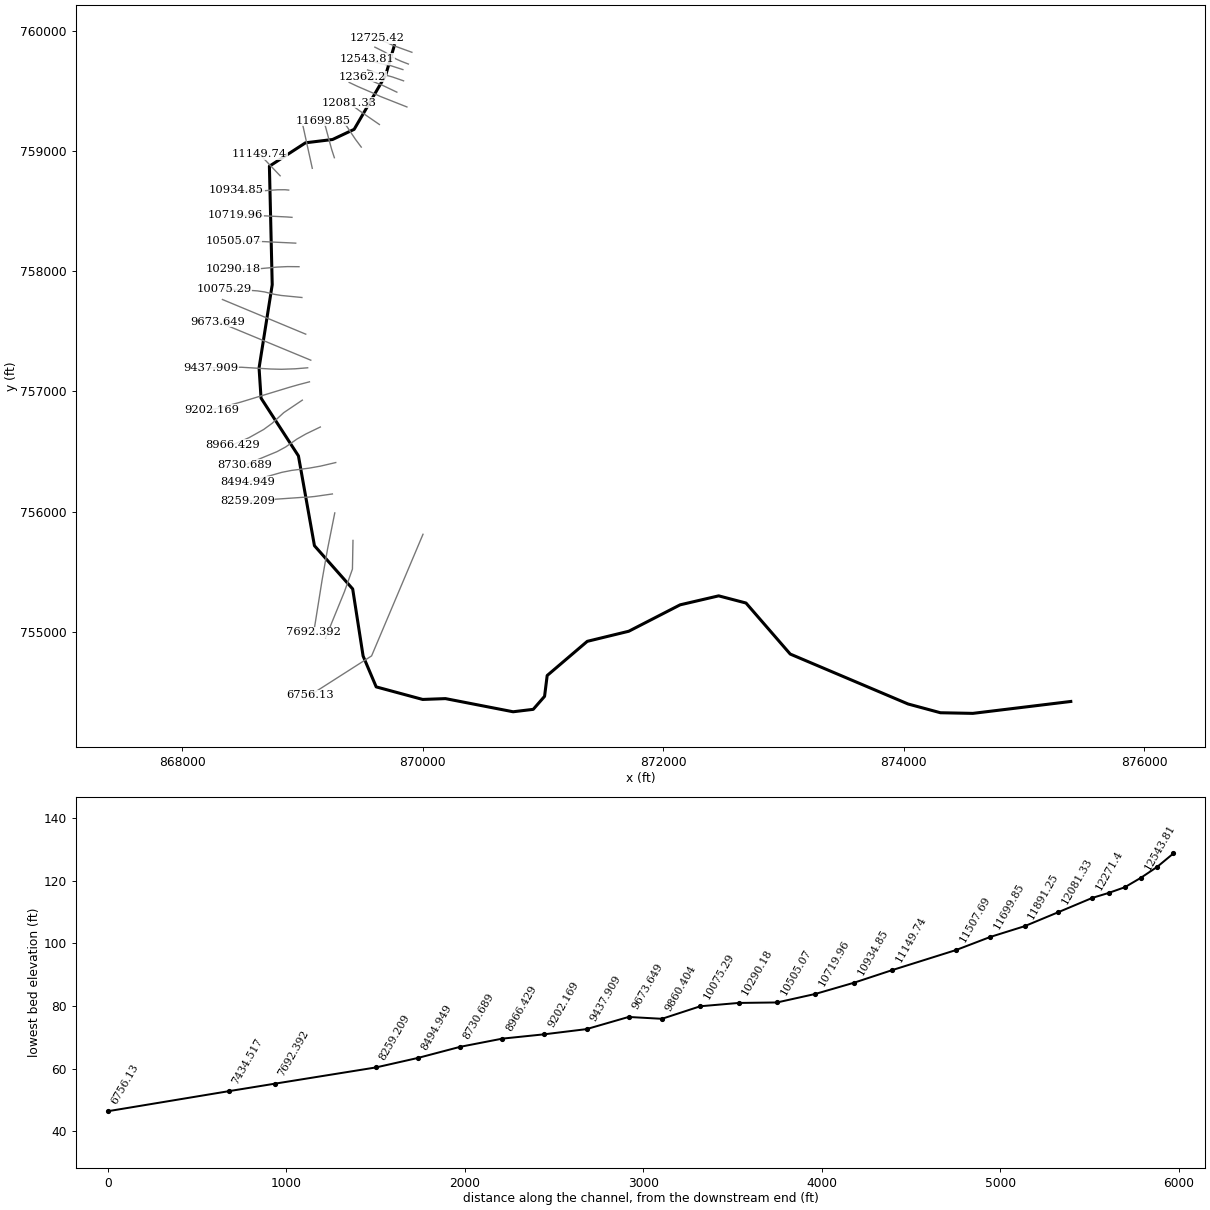
--- 9116_ras.prj (project) ---

Proj Title=9116
Current Plan=p01
Default Exp/Contr=0.3,0.1
English Units
Geom File=g01
Flow File=f01
Plan File=p01
Y Axis Title=Elevation
X Axis Title(PF)=Main Channel Distance
X Axis Title(XS)=Station
BEGIN DESCRIPTION:
RFD model 9116 exported to HEC-RAS
END DESCRIPTION:

--- 9116_ras.p01 (plan) ---

Plan Title=Plan 01
Program Version=4.10
Short Identifier=Plan 01
Geom File=g01
Flow File=f01
Subcritical Flow
Calc Critical at every XS
Secant Critical Depth

--- 9116_ras.f01 (steady flow) ---

Flow Title=Flow 01
Program Version=5.01
Number of Profiles= 6
Profile Names=10yr,25yr,50yr,100yr,100plus,500yr
River Rch & RM=9116,33,12725.42
  160.94  251.13  333.49  406.33  593.24 1012.27
River Rch & RM=9116,33,11699.85
  165.95  258.99  343.98  419.15  611.95 1039.79
River Rch & RM=9116,33,11507.69
  172.72  269.62  358.17  436.48  637.27 1076.86
River Rch & RM=9116,33,11149.74
   271.3  424.09  564.09  687.75 1004.12 1592.06
River Rch & RM=9116,33,10934.85
  332.56  520.32  692.62  844.78 1233.38 1900.72
River Rch & RM=9116,33,10719.96
  339.23  530.81  706.64  861.93 1258.42 1933.99
River Rch & RM=9116,33,10505.07
  357.73     560  745.74  909.82 1328.33 2026.73
River Rch & RM=9116,33,10290.18
   363.9  569.71  758.73  925.71 1351.54 2057.28
River Rch & RM=9116,33,10075.29
  465.54  729.93  973.28 1188.31 1734.94 2552.65
River Rch & RM=9116,33,9860.404
   468.4  734.46  979.37 1195.79 1745.85 2566.63
River Rch & RM=9116,33,9673.649
  476.23  746.88  996.06  1216.3 1775.79 2604.91
River Rch & RM=9116,33,9437.909
  495.41  777.27  1036.9 1266.42 1848.97 2697.95
River Rch & RM=9116,33,9202.169
  523.05  821.28 1096.22 1339.44 1955.58 2833.53
River Rch & RM=9116,33,8966.429
   524.1  822.94 1098.45 1342.18 1959.58 2838.56
River Rch & RM=9116,33,8730.689
  531.79  835.12 1114.81 1362.26  1988.9 2875.37
River Rch & RM=9116,33,8494.949
  558.39  877.32 1171.57 1431.97 2090.68 3002.78
River Rch & RM=9116,33,8259.209
  561.11  881.65  1177.4 1439.14 2101.15  3015.9
River Rch & RM=9116,33,7692.392
  793.45 1249.43 1671.43 2045.12 2985.88 4086.07
River Rch & RM=9116,33,7434.517
  795.91 1253.38 1676.78 2051.73 2995.53 4097.69
River Rch & RM=9116,33, 6756.13
 1226.18 1940.17 2604.67 3195.15 4664.92 6025.17
River Rch & RM=9116,33,6224.797
 1236.37 1956.61 2627.04 3222.89 4705.43 6071.28
River Rch & RM=9116,33,5770.307
  1250.1 1978.77 2657.21 3260.31 4760.06 6133.38
River Rch & RM=9116,33,5279.291
  1252.8 1983.15 2663.18 3267.74  4770.9 6145.77
Boundary for River Rch & Prof#=9116,33,1
Up Type= 0
Dn Type= 2
Boundary for River Rch & Prof#=9116,33,2
Up Type= 0
Dn Type= 2
Boundary for River Rch & Prof#=9116,33,2
Up Type= 0
Dn Type= 2
Boundary for River Rch & Prof#=9116,33,2
Up Type= 0
Dn Type= 2
Boundary for River Rch & Prof#=9116,33,2
Up Type= 0
Dn Type= 2
Boundary for River Rch & Prof#=9116,33,2
Up Type= 0
Dn Type= 2

--- 9116_ras.g01 (geometry) ---

Geom Title=9116
Program Version=4.10

River Reach=9116,33
Reach XY= 30
869764.272820514 759874.78336469869692.304363951759628.846689089
869430.561880092   759179.399286869250.787188729 759094.80181747
869026.542667591759067.510000567868725.984919493758872.770300163
868749.422419514757887.527244633868640.047419505757195.686966846
868656.540475048756944.818911274868967.388565174756464.415997809
869100.468979925755717.834835768 869418.45188497 755358.08803086
869504.963108283754800.864959413869613.805792555754544.040421509
870000.290475051754439.610577991870189.526586167 754446.55502242
870752.026586163754337.180022461870919.433270195754357.284912499
871013.683657506754465.350214706871035.383086256754638.519216128
871368.689212811754922.669101744871713.704103559755006.590468055
872140.787436871755226.208523555872461.099936919755300.861301319
872688.327786427755241.248008847873056.021818131754816.943108147
 874035.48409787754401.908781723874305.006565633754329.000280852
874574.297197169754323.771931477875388.574166268754422.811963209

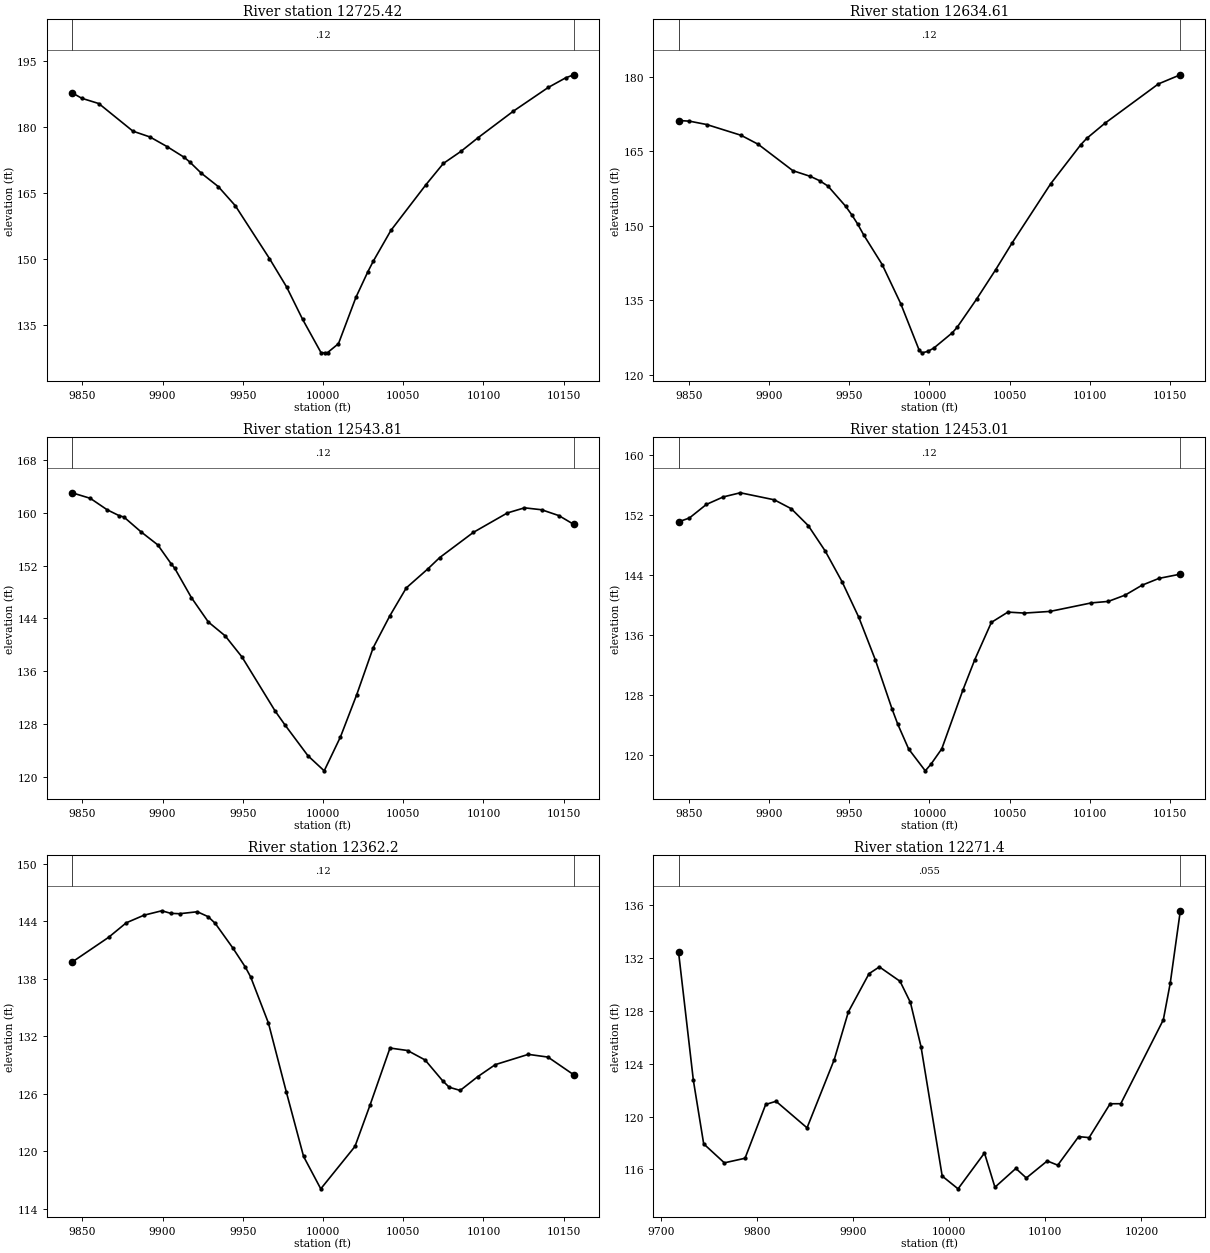
Type RM Length L Ch R = 1 ,12725.42,90.803100,90.803100,90.803100
XS GIS Cut Line= 5
869910.676359209759819.975828318869775.619449069759868.942133641
869764.787728975759873.466220326869762.955676149759874.268456229
869620.323332358759935.925968885
#Sta/Elev= 30
9843.602187.8016 9849.64186.55319860.277185.35199881.551179.07949892.188177.7602
9902.825175.57419913.462 173.1539917.019172.06289924.099169.55329934.736166.4975
9945.372162.14099966.646150.15099977.283143.72529987.261136.3745 9998.77128.7875
   10001128.730510002.84 128.77910009.67130.813510020.56141.353710028.05147.2026
10031.46149.615510042.35 156.54110064.14166.898710075.03171.745610085.93174.4703
10096.82177.637510118.61183.6042 10140.4189.002510151.29191.194910156.39191.8887
#Mann= 3 , 0 , 0
9843.602    0.12       09843.602    0.12       010156.39    0.12       0
#XS Ineff= 2 , 0
       0                               0
Bank Sta=9843.602,10156.39
Exp/Cntr=0.3,0.1

Type RM Length L Ch R = 1 ,12634.61,90.803200,90.803200,90.803200
XS GIS Cut Line= 6
869881.348174498759722.306404214869822.384979477 759744.95330801
 869781.36520163759763.197718175869737.058893242759788.550731414
869683.241890329759822.554559101869602.768263862759862.708148132
#Sta/Elev= 30
9843.637171.15649850.437171.0269 9861.15170.35219882.574168.18919893.286166.3779
9914.882161.07389925.827159.91959931.522159.06499936.771157.97529947.716153.9438
9951.694152.15279955.306150.32759959.039148.15099970.578 142.1859982.117134.3393
9993.656124.9487 9995.39 124.447    9999124.737910002.74125.406910014.23128.4697
10017.32129.601410029.41135.2521 10041.2141.120210051.54146.545310075.65158.4754
10094.31166.2821   10098167.555610109.18170.5574 10142.7178.511410156.37180.3514
#Mann= 3 , 0 , 0
9843.637    0.12       09843.637    0.12       010156.37    0.12       0
#XS Ineff= 2 , 0
       0                               0
Bank Sta=9843.637,10156.37
Exp/Cntr=0.3,0.1

Type RM Length L Ch R = 1 ,12543.81,90.803200,90.803200,90.803200
XS GIS Cut Line= 6
869835.811155146759676.013374261869730.364061262759710.051889049
869700.789362833759716.945648904869660.248765176759723.555442648
 869621.79901629759733.314306658869536.227636384759763.657030261
#Sta/Elev= 30
9843.629163.0079 9854.99162.16879865.498160.43729872.883159.55959876.006159.3286
9886.514157.12029897.022155.13639905.436152.2506 9907.53 151.6299918.038147.1429
9928.546143.47329939.054141.37679949.562138.1711 9970.21130.00349976.231127.9369
9990.662123.242910000.77120.967410010.91126.100710021.06132.4998 10031.3139.5826
10041.62144.378610051.93148.625710065.55151.5402 10072.7153.199410093.72157.0184
10114.91 159.956 10125.6160.7324 10136.3  160.4410146.99159.559810156.37158.2233
#Mann= 3 , 0 , 0
9843.629    0.12       09843.629    0.12       010156.37    0.12       0
#XS Ineff= 2 , 0
       0                               0
Bank Sta=9843.629,10156.37
Exp/Cntr=0.3,0.1

Type RM Length L Ch R = 1 ,12453.01,90.803200,90.803200,90.803200
XS GIS Cut Line= 6
869841.380869135759582.614664066869747.926630376 759615.04200924
869693.469041954759629.928367318869691.489142966759630.211210027
869619.499393028759648.097180698869542.321082052759673.292868077
#Sta/Elev= 30
9843.624151.04869850.378151.55589860.963153.36059871.548154.36449882.133 154.912
9903.303153.97719913.888152.79169924.472150.54699935.057147.16089945.578143.0674
9955.945138.36199966.312132.67329976.679126.16899980.309124.10629987.046120.8372
9997.413 117.929   10001 118.82710007.69120.858110020.86128.676610028.29132.7293
 10038.6137.6736 10048.9139.041910059.21 138.91110075.18139.133510100.95140.2674
10111.47140.463410121.99 141.30410132.51142.619610143.03143.524210156.37  144.09
#Mann= 3 , 0 , 0
9843.624    0.12       09843.624    0.12       010156.37    0.12       0
#XS Ineff= 2 , 0
       0                               0
Bank Sta=9843.624,10156.37
Exp/Cntr=0.3,0.1

Type RM Length L Ch R = 1 , 12362.2,90.803300,90.803300,90.803300
XS GIS Cut Line= 6
869785.510783435759488.551407413869662.276543651759547.229077771
869644.661083027759554.055650564869642.745430455759554.630346333
869623.278971959759561.915270869869500.243195321759616.509712257
#Sta/Elev= 30
9843.617139.72599866.334142.3034 9877.41143.82429888.486144.61829899.562145.0768
 9905.14144.80959910.637 144.7719921.713144.97479928.401144.46489932.789143.7783
9943.864141.18969951.662139.1962 9954.94138.17959966.016133.37569977.092 126.242
9987.912119.47819998.637116.099210019.95120.517310029.39124.849110041.78130.7725
10052.72130.515110063.66129.5291 10074.6 127.361 10078.7126.685510085.54126.3547
10096.48127.790110107.42 129.04410128.01 130.11310140.25129.829510156.39127.9765
#Mann= 3 , 0 , 0
9843.617    0.12       09843.617    0.12       010156.39    0.12       0
#XS Ineff= 2 , 0
       09926.587        10046.12       0
Bank Sta=9843.617,10156.39
Exp/Cntr=0.3,0.1

Type RM Length L Ch R = 1 , 12271.4,190.073800,190.073800,190.073800
XS GIS Cut Line= 6
869869.334886121759365.470268336869646.378032509759453.561551953
869581.957274592759483.365035438869530.558319486759505.432783033
 869458.05305608759536.728932968869389.009635519759569.493334094
#Sta/Elev= 30
9718.453132.43969733.867122.74359744.619117.93469766.123116.49949787.628116.8467
9809.132120.91389819.885121.15219852.141119.14599880.456124.3053 9895.15 127.913
9916.655130.80069927.407131.31099948.912130.2221  9959.7128.62289970.719125.2795
9992.755 115.49910009.24114.534410036.74117.244610047.62114.655710069.39116.0765
10080.27115.355410102.04116.643110112.94116.323210134.72118.482410145.61118.4061
10167.45120.964610178.52120.969610222.79127.308910230.01130.087110240.49135.5535
#Mann= 3 , 0 , 0
9718.453   0.055       09718.453   0.055       010240.49   0.055       0
#XS Ineff= 2 , 0
       09949.641        10032.31       0
Bank Sta=9718.453,10240.49
Exp/Cntr=0.3,0.1

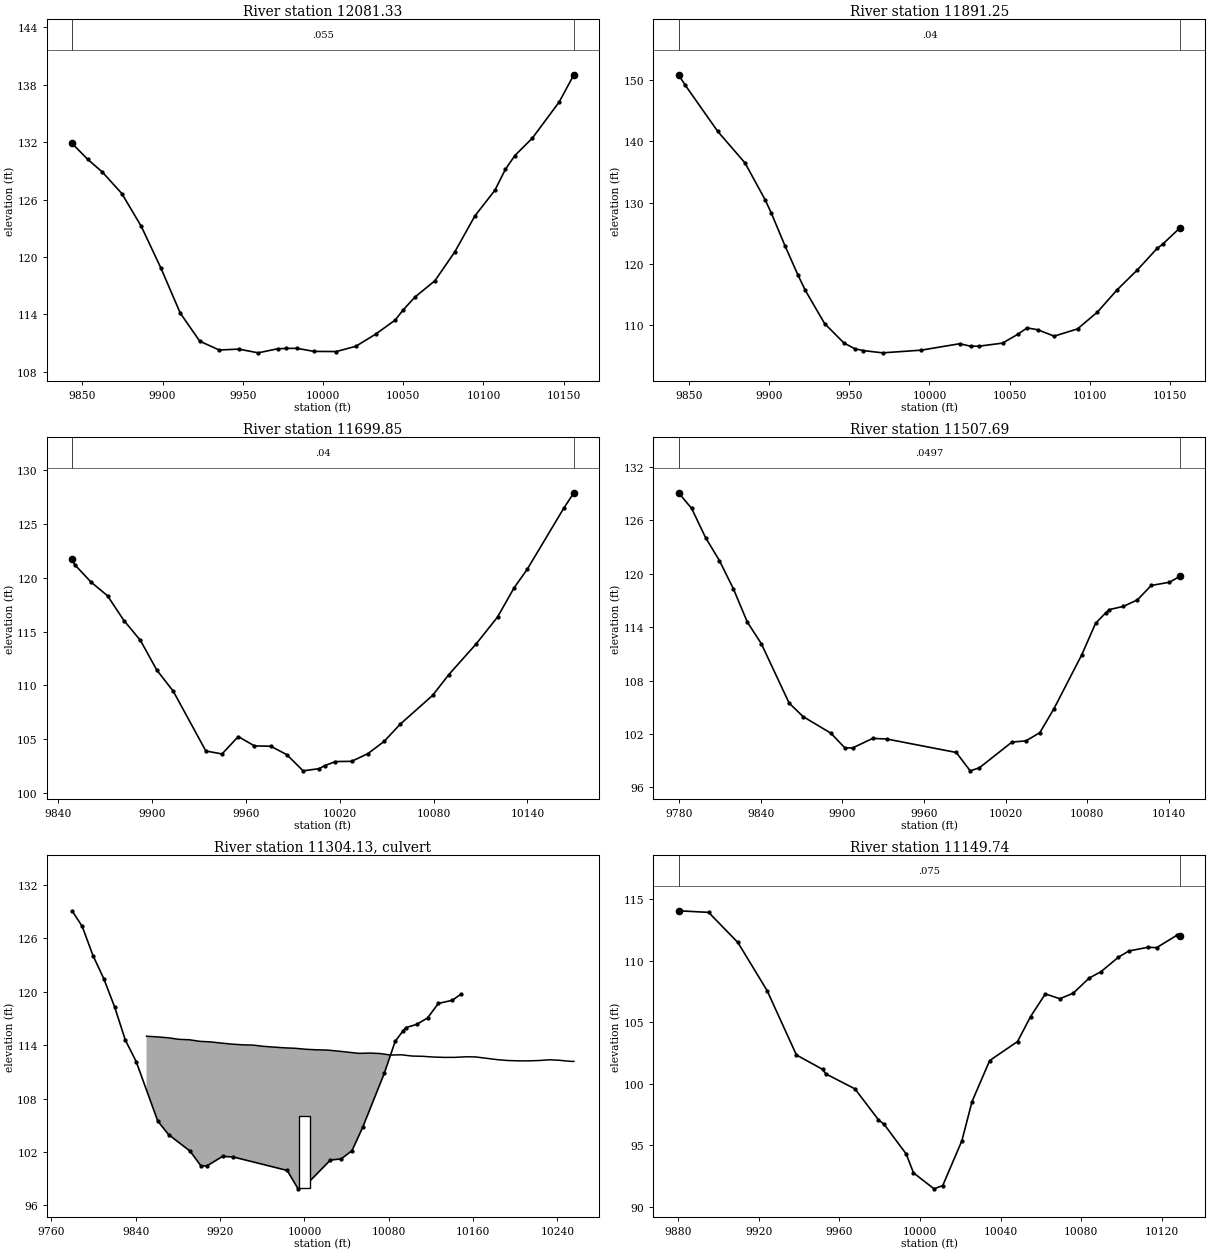
Type RM Length L Ch R = 1 ,12081.33,190.073900,190.073900,190.073900
XS GIS Cut Line= 5
869640.528699582759219.485102455869512.561774512759307.654780122
869510.937776042759308.822097118869470.882307439759337.109630625
869385.433385958759400.432561899
#Sta/Elev= 30
9843.599131.86319853.319130.20159862.457128.87369874.601126.62359886.745123.1919
9898.888118.86929911.032114.13569923.176111.1961 9935.32 110.2729947.464110.3678
9959.608109.97829971.751110.40419976.696110.43899983.895110.44919994.321110.1294
10008.27110.112310020.51110.665910032.75111.9211   10045113.401410050.04114.4731
10057.36115.806910069.81117.517810082.25120.5458 10094.7124.286310107.14126.9575
10113.68129.142510119.59130.588710130.47132.404210147.27136.196910156.39139.0331
#Mann= 3 , 0 , 0
9843.599   0.055       09843.599   0.055       010156.39   0.055       0
#XS Ineff= 2 , 0
       0                               0
Bank Sta=9843.599,10156.39
Exp/Cntr=0.3,0.1

Type RM Length L Ch R = 1 ,11891.25,191.402300,191.402300,191.402300
XS GIS Cut Line= 6
869489.617748213759031.769563768869441.409241315759096.228379559
869399.745198196759158.462749145869398.666077804759160.146643197
869374.051500406759197.309238753 869308.43753032759286.617974832
#Sta/Elev= 30
9843.614150.87499847.648149.23559868.021141.64219885.111136.45849897.598130.4652
9901.415128.31189910.085122.87989918.111 118.1529922.573115.70499934.663110.2575
9946.697107.08559953.603106.12819958.731 105.8439970.765105.47379994.833105.9096
10018.82106.959710025.75106.554710030.81106.558910045.58107.058810055.12108.5095
10060.86109.541710067.53109.245310077.75108.196710092.34109.384110104.75112.1391
10117.16115.809510129.57118.999410141.98122.540410145.31123.1937 10156.4125.9341
#Mann= 3 , 0 , 0
9843.614    0.04       09843.614    0.04       0 10156.4    0.04       0
#XS Ineff= 2 , 0
       09982.375                       0
Bank Sta=9843.614,10156.4
Exp/Cntr=0.3,0.1

Type RM Length L Ch R = 1 ,11699.85,192.163300,192.163300,192.163300
XS GIS Cut Line= 6
869266.100196235758943.447166281869243.597012125759012.488477599
869220.744082659759096.300089785869220.210292742759098.227541036
869192.911252193759199.730973097869175.368156878759251.202516455
#Sta/Elev= 30
9848.749121.74159850.382121.2369  9860.9119.60289871.418118.33449881.935116.0322
9892.453114.19039902.971 111.4229913.489109.45779934.333103.90389944.698103.6293
9955.063105.24729965.429104.37559975.794104.34939986.159103.56019996.524102.0595
10006.89102.264610010.24102.538110017.25102.9217 10027.6102.944110037.96103.6571
10048.32104.790710058.67106.398710079.38109.074310089.74111.0055 10107.3113.8686
10120.91116.358210131.48119.066910139.87120.787710163.17126.449610169.73127.9079
#Mann= 3 , 0 , 0
9848.749    0.04       09848.749    0.04       010169.73    0.04       0
#XS Ineff= 2 , 0
       09972.055                       0
Bank Sta=9848.749,10169.73
Exp/Cntr=0.3,0.1

Type RM Length L Ch R = 1 ,11507.69,357.948000,357.948000,357.948000
XS GIS Cut Line= 2
869082.464465698758855.608072634869003.267931028759215.865374671
#Sta/Elev= 30
9779.553129.06979789.169127.32099799.408124.04279809.647121.45049819.886118.2921
9830.125114.55579840.363112.15159860.841105.4756 9871.08103.95879891.557102.0927
9901.796 100.447 9907.47100.43739922.274101.50889932.512101.44319983.70699.92972
9993.94597.8690110000.6298.2017310024.66101.0982 10034.9101.228110045.14102.1521
10055.38104.802910075.86110.859410086.09114.416510093.77115.629510096.33115.9625
10106.57 116.32410116.81117.046410127.05118.670110140.35119.030310148.41119.7095
#Mann= 3 , 0 , 0
9779.553  0.0497       09779.553  0.0497       010148.41  0.0497       0
#XS Ineff= 2 , 0
       09979.481         10030.9       0
Bank Sta=9779.553,10148.41
Exp/Cntr=0.3,0.1

Type RM Length L Ch R = 2 ,11304.13,,,
Bridge Culvert--1,0,-1,-1, 0
Deck Dist Width WeirC Skew NumUp NumDn MinLoCord MaxHiCord MaxSubmerge Is_Ogee
16.474,325,2.6,0,48,48, , , 0.95, 0, 0,0,,
 9850.20 9850.44 9860.50 9870.56 9880.63 9887.63 9890.69 9900.76 9910.82 9920.89
 9930.95 9941.01 9951.08 9961.14 9971.21 9976.33 9981.27 9991.3310001.4010011.46
10021.5310031.5910041.6610051.7210061.7810065.0310071.8510081.9110091.9810102.04
10112.1010122.1710132.2310142.3010152.3610153.7210162.4310172.4910182.5510192.62
10202.6810212.7510222.8110232.8710242.4210242.9410253.0010255.61
  115.00  114.99  114.92  114.82  114.65  114.61  114.60  114.42  114.36  114.23
  114.11  114.03  114.00  113.86  113.77  113.73  113.69  113.64  113.53  113.47
  113.44  113.33  113.20  113.07  113.10  113.09  113.05  112.88  112.91  112.77
  112.74  112.66  112.62  112.62  112.68  112.69  112.67  112.52  112.37  112.27
  112.23  112.23  112.27  112.35  112.29  112.28  112.17  112.17
                                                                                
                                                                                
                                                                                
                                                                                
                                                                
 9850.20 9850.44 9860.50 9870.56 9880.63 9887.63 9890.69 9900.76 9910.82 9920.89
 9930.95 9941.01 9951.08 9961.14 9971.21 9976.33 9981.27 9991.3310001.4010011.46
10021.5310031.5910041.6610051.7210061.7810065.0310071.8510081.9110091.9810102.04
10112.1010122.1710132.2310142.3010152.3610153.7210162.4310172.4910182.5510192.62
10202.6810212.7510222.8110232.8710242.4210242.9410253.0010255.61
  115.00  114.99  114.92  114.82  114.65  114.61  114.60  114.42  114.36  114.23
  114.11  114.03  114.00  113.86  113.77  113.73  113.69  113.64  113.53  113.47
  113.44  113.33  113.20  113.07  113.10  113.09  113.05  112.88  112.91  112.77
  112.74  112.66  112.62  112.62  112.68  112.69  112.67  112.52  112.37  112.27
  112.23  112.23  112.27  112.35  112.29  112.28  112.17  112.17
                                                                                
                                                                                
                                                                                
                                                                                
                                                                
BR Coef=-1 , 0 , 0 ,, 0 ,,,0.8,-1,,0,
WSPro=,,,, 1 ,,,, 0 ,,,, 0 ,,,,-1 ,-1 ,-1 , 0 , 0 , 0 , 0 , 0
Culvert=2,8,10,325,0.013,0.5,1,8,3,98,10000,92,10000,Culvert #1, 0, 16.474
Culvert Bottom n=0.013
BC Design=,, 0 ,, 0 ,,,,,,

Type RM Length L Ch R = 1 ,11149.74,214.889300,214.889300,214.889300
XS GIS Cut Line= 2
868815.276782998758793.191131081868643.837493161758973.494877091
#Sta/Elev= 30
 9880.27114.05639895.184113.92669909.696111.47869924.162107.57479938.721102.3353
 9951.76101.16179953.233100.80589967.74699.580989979.35897.077469982.25896.68612
9993.15794.28565 9996.77 92.751110006.9691.4546110011.2891.7244110020.7595.35846
 10025.898.5524810034.55101.883110048.35103.426510054.82105.457510062.15107.3001
10069.33106.906610075.95107.353610083.84108.583710089.75109.105410098.36110.2824
10103.55110.786210112.87 111.08510117.35111.062710127.38112.064910129.07111.9729
#Mann= 3 , 0 , 0
 9880.27   0.075       0 9880.27   0.075       010129.07   0.075       0
#XS Ineff= 2 , 0
       0                               0
Bank Sta=9880.27,10129.07
Exp/Cntr=0.3,0.1

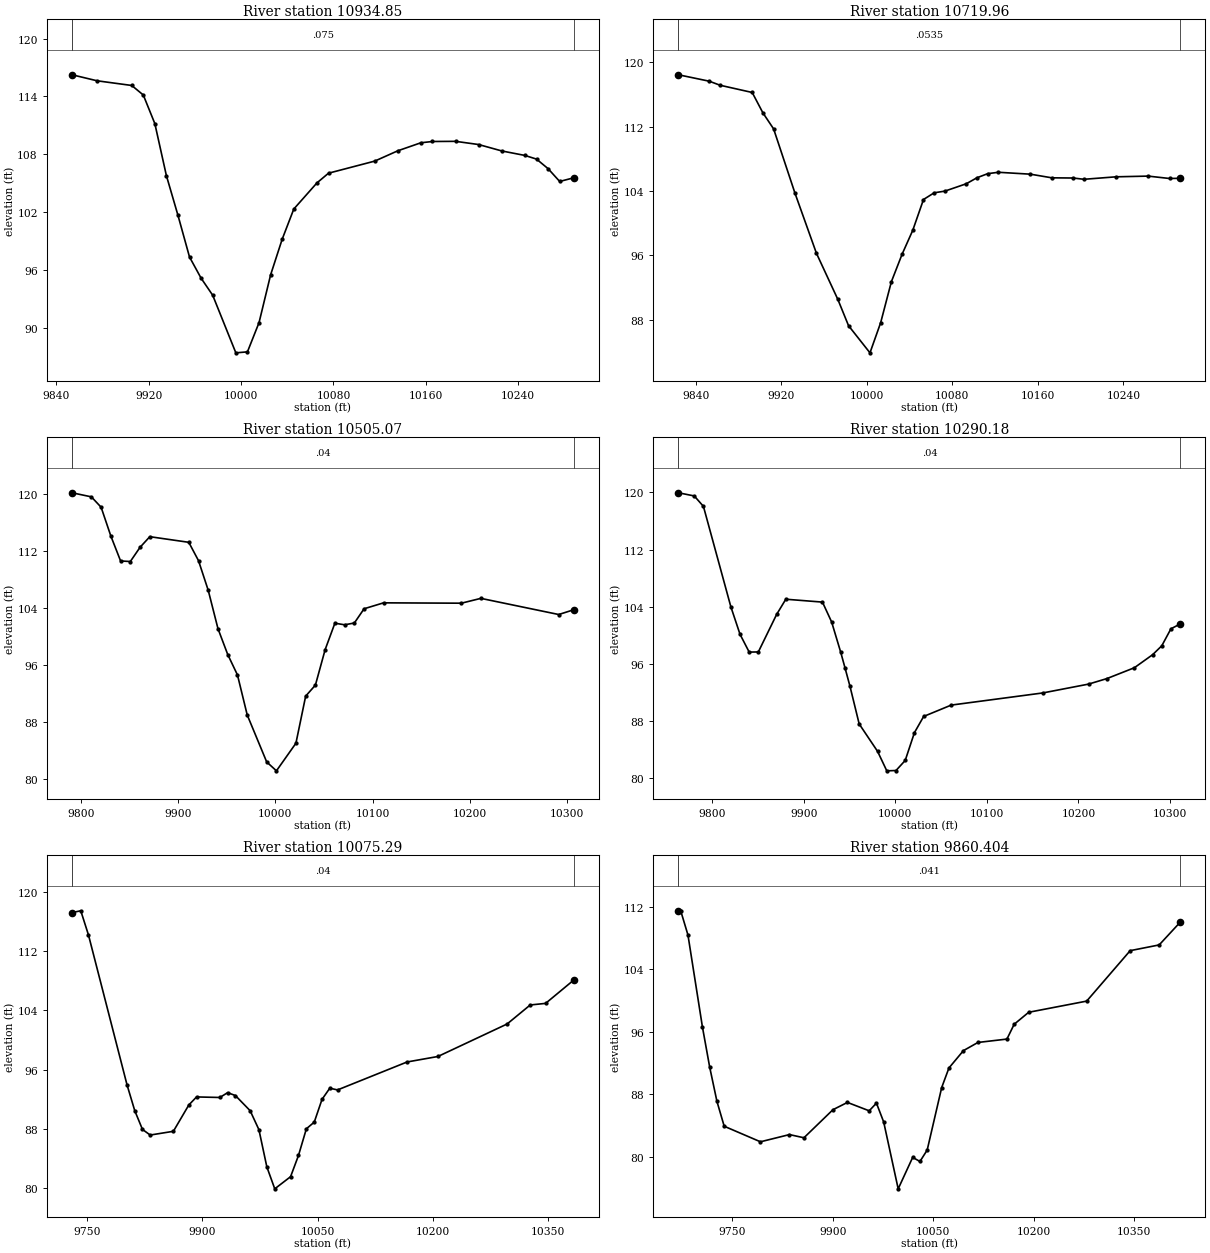
Type RM Length L Ch R = 1 ,10934.85,214.889300,214.889300,214.889300
XS GIS Cut Line= 6
868886.568834414758674.348435619868856.562447217758677.228256822
868795.073414384758676.912967154868611.160960445758664.024254517
868527.972686602758665.987379311868452.707109198758672.095447691
#Sta/Elev= 30
9853.577116.24989875.245115.62669905.284115.14049915.284114.15169925.284111.1861
9935.285105.79379945.285101.6852 9955.3297.349889965.35595.15248 9975.3993.38803
9995.46187.4098810005.5187.5112810015.5590.5426810025.5995.5006610035.6399.20204
10045.67 102.32610065.73105.036610075.74106.041310115.77107.295310135.79108.3665
10155.79109.1983 10165.8109.3299 10185.8109.346410205.81109.014710225.85108.3498
10245.92107.882710255.95107.503410265.98106.511210276.02105.185710288.35105.5692
#Mann= 3 , 0 , 0
9853.577   0.075       09853.577   0.075       010288.35   0.075       0
#XS Ineff= 2 , 0
       0                               0
Bank Sta=9853.577,10288.35
Exp/Cntr=0.3,0.1

Type RM Length L Ch R = 1 ,10719.96,214.889200,214.889200,214.889200
XS GIS Cut Line= 6
868913.808968134758447.731607425868866.029266577758451.168115281
868738.998390078758457.452951315868737.002819761758457.585989354
868696.533886863758459.714311864868444.891963883 758466.86167542
#Sta/Elev= 30
9823.911118.43999852.794117.6378 9862.82117.13839892.869116.23839902.881113.7009
9912.893111.70739932.918103.69369952.94296.238359972.96790.500459982.97987.22911
10003.01 83.854810013.02  87.60810023.0392.7012310033.0596.1204910043.0699.10637
10053.06102.925710063.07 103.76110073.07103.969210093.08104.884310103.08105.6323
10113.09106.139410123.09 106.313 10153.1106.075710173.11105.623210193.12105.5992
10203.12105.440410233.14105.748710263.15 105.83710283.16105.540610293.27105.5626
#Mann= 3 , 0 , 0
9823.911  0.0535       09823.911  0.0535       010293.27  0.0535       0
#XS Ineff= 2 , 0
       0                               0
Bank Sta=9823.911,10293.27
Exp/Cntr=0.3,0.1

Type RM Length L Ch R = 1 ,10505.07,214.889300,214.889300,214.889300
XS GIS Cut Line= 6
868944.808129215758233.137257054868941.703253159 758233.35470872
868737.094316064758242.940268714868735.098948673758243.076316483
868686.135908881758245.744089246868429.388274342758251.737561485
#Sta/Elev= 30
9791.054120.11179810.888119.54059820.899 118.087 9830.91114.04779840.921 110.553
9850.932110.47529860.943112.47049870.954113.95669910.998113.16879921.009110.5934
 9931.02106.42829941.031 101.0529951.04297.438789961.05394.566649971.06488.96541
9991.08682.37488 10001.181.1290910021.1385.0000510031.1491.6013310041.1693.15124
10051.1798.1263310061.17101.826710071.18101.603610081.18101.855510091.18103.8503
10111.19104.681510191.21104.632310211.22105.309210291.24103.044710306.85103.7206
#Mann= 3 , 0 , 0
9791.054    0.04       09791.054    0.04       010306.85    0.04       0
#XS Ineff= 2 , 0
       0                               0
Bank Sta=9791.054,10306.85
Exp/Cntr=0.3,0.1

Type RM Length L Ch R = 1 ,10290.18,214.889300,214.889300,214.889300
XS GIS Cut Line= 6
868972.247121585758037.383949867868876.145575839758038.174928003
868790.281111866758034.220325543 868639.49609755758020.180086852
868550.754255245758018.634157866868424.755506255 758020.71133069
#Sta/Elev= 30
9763.003119.9608 9780.26119.5149 9790.26118.0555 9820.26103.9648 9830.26100.1149
 9840.2697.62475 9850.2697.645369870.272102.90879880.283105.03679920.325104.6332
9930.336101.84979940.34697.57106 9945.0795.362159950.38192.830579960.43887.54889
9980.55183.702339990.60780.9753610000.67 81.021610010.74 82.433410020.8186.33122
10030.88 88.600710060.9790.1924110161.0591.8959710211.0693.1357910231.0693.90854
10261.0795.4275610281.0797.2611310291.0798.5091810301.07100.893710311.32101.5738
#Mann= 3 , 0 , 0
9763.003    0.04       09763.003    0.04       010311.32    0.04       0
#XS Ineff= 2 , 0
       09900.213                       0
Bank Sta=9763.003,10311.32
Exp/Cntr=0.3,0.1

Type RM Length L Ch R = 1 ,10075.29,214.889300,214.889300,214.889300
XS GIS Cut Line= 6
868996.293207021 757781.29484029868823.992576532757798.194418426
 868766.09736245757807.904033884868685.093711585757827.725222256
868625.201924821757836.427897353868348.181862946 757854.79501427
#Sta/Elev= 30
9730.325117.16539741.661117.40849751.698114.13989801.88593.935319811.92390.46107
 9821.9887.925299832.03887.169769862.21587.674089882.33291.222949892.39192.30848
9922.72192.23472 9932.86 92.8855    994392.494069962.16790.451769973.60587.89285
9983.91282.878359994.21979.9164210014.8281.55652 10025.184.4124110035.3888.01343
10045.6688.9144510055.76 91.980710065.87 93.486410075.9793.2534310166.49 97.0212
10206.6397.7612410296.77102.144910326.82104.706910346.85104.921910383.73 108.086
#Mann= 3 , 0 , 0
9730.325    0.04       09730.325    0.04       010383.73    0.04       0
#XS Ineff= 2 , 0
       0 9938.16                       0
Bank Sta=9730.325,10383.73
Exp/Cntr=0.3,0.1

Type RM Length L Ch R = 1 ,9860.404,186.755600,186.755600,186.755600
XS GIS Cut Line= 2
869028.072525309757476.480735147868335.820876508757764.469955285
#Sta/Elev= 30
9669.488 111.4079672.816 111.4789683.647108.38299705.30896.597659716.13991.46844
 9726.9787.090619737.80183.915379791.95581.925469835.27882.84742 9856.9482.44094
9900.26386.030149921.92586.962419954.41885.887849965.24886.873759976.07984.45807
9997.74175.90721 10019.479.9316610030.2379.4059510041.0680.8679210062.7388.86432
10073.5691.3671510095.2293.5887310116.8894.63295 10160.295.0652910171.0396.96163
 10192.798.4933710279.3499.9221110344.33106.376410387.65107.109710419.25110.0333
#Mann= 3 , 0 , 0
9669.488   0.041       09669.488   0.041       010419.25   0.041       0
#XS Ineff= 2 , 0
       09951.743                       0
Bank Sta=9669.488,10419.25
Exp/Cntr=0.3,0.1

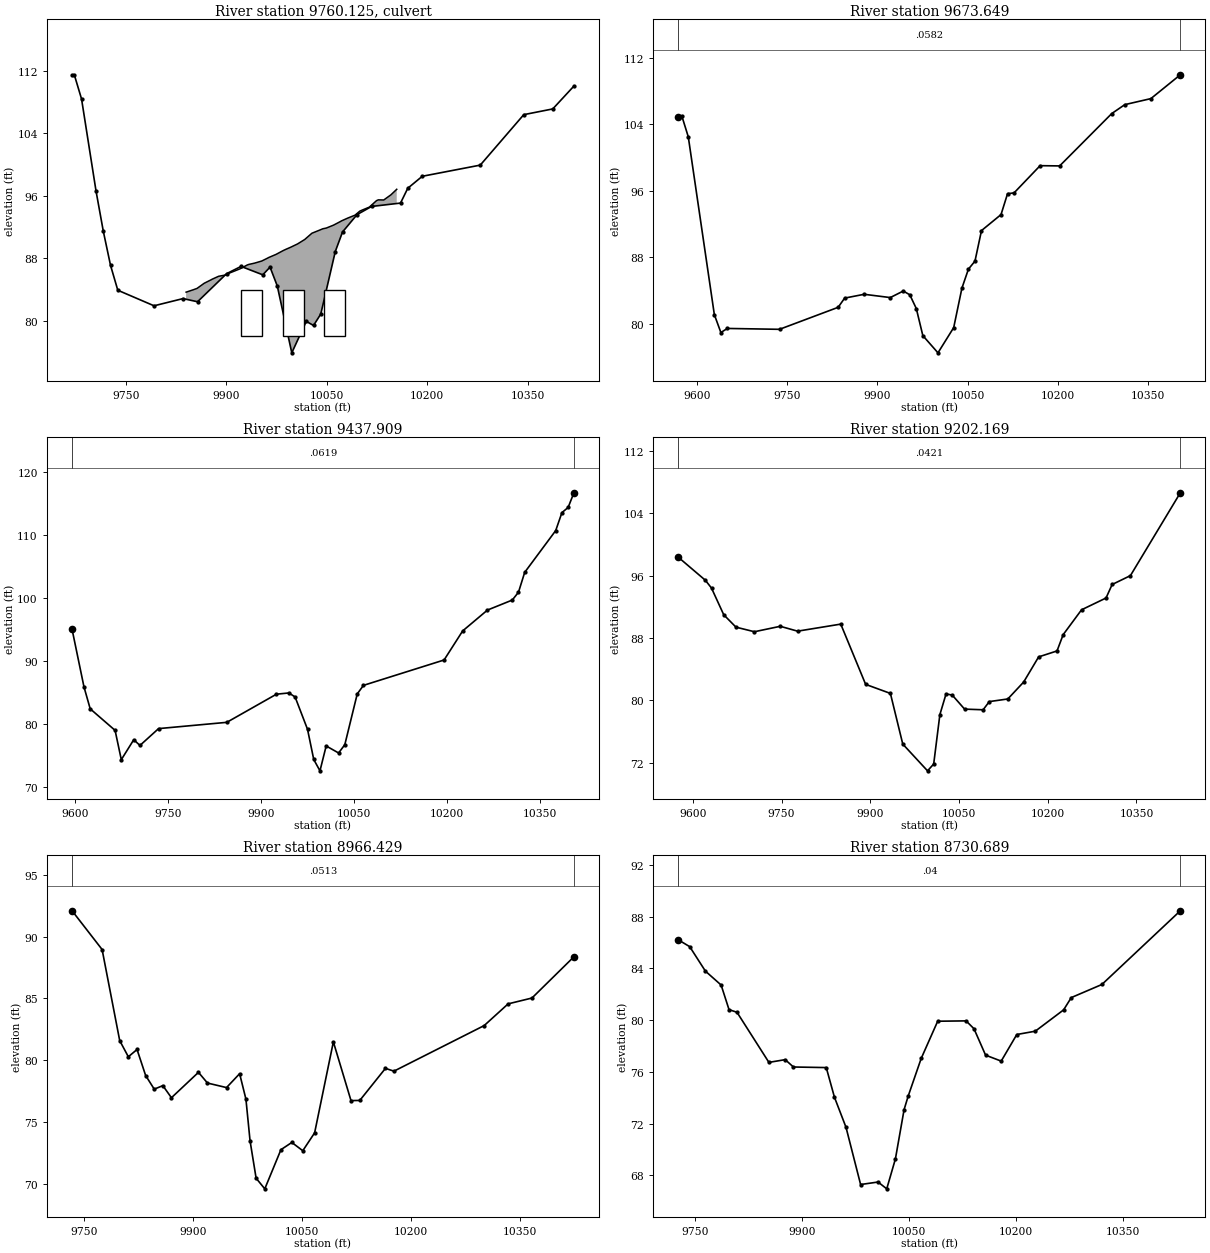
Type RM Length L Ch R = 2 ,9760.125,,,
Bridge Culvert--1,0,-1,-1, 0
Deck Dist Width WeirC Skew NumUp NumDn MinLoCord MaxHiCord MaxSubmerge Is_Ogee
26.378,134,2.6,0,42,42, , , 0.95, 0, 0,0,,
 9839.86 9845.46 9850.71 9856.18 9866.91 9877.64 9878.35 9888.36 9899.09 9905.98
 9909.82 9920.55 9931.27 9933.62 9942.00 9952.73 9961.26 9963.45 9974.18 9984.91
 9988.90 9995.6310006.3610016.5310017.0910027.8110038.5410044.1710049.2710059.99
10070.7210071.8110081.4510092.1710099.4410102.9010113.6310124.3510127.0810135.08
10145.8110154.55
   83.67   83.83   83.98   84.15   84.81   85.27   85.31   85.70   85.87   86.16
   86.29   86.66   87.15   87.22   87.38   87.65   88.01   88.11   88.50   88.99
   89.15   89.40   89.84   90.38   90.41   91.21   91.58   91.78   91.87   92.24
   92.72   92.78   93.15   93.52   94.04   94.17   94.55   95.38   95.48   95.46
   96.12   96.83
                                                                                
                                                                                
                                                                                
                                                                                
                
 9839.86 9845.46 9850.71 9856.18 9866.91 9877.64 9878.35 9888.36 9899.09 9905.98
 9909.82 9920.55 9931.27 9933.62 9942.00 9952.73 9961.26 9963.45 9974.18 9984.91
 9988.90 9995.6310006.3610016.5310017.0910027.8110038.5410044.1710049.2710059.99
10070.7210071.8110081.4510092.1710099.4410102.9010113.6310124.3510127.0810135.08
10145.8110154.55
   83.67   83.83   83.98   84.15   84.81   85.27   85.31   85.70   85.87   86.16
   86.29   86.66   87.15   87.22   87.38   87.65   88.01   88.11   88.50   88.99
   89.15   89.40   89.84   90.38   90.41   91.21   91.58   91.78   91.87   92.24
   92.72   92.78   93.15   93.52   94.04   94.17   94.55   95.38   95.48   95.46
   96.12   96.83
                                                                                
                                                                                
                                                                                
                                                                                
                
BR Coef=-1 , 0 , 0 ,, 0 ,,,0.8,-1,,0,
WSPro=,,,, 1 ,,,, 0 ,,,, 0 ,,,,-1 ,-1 ,-1 , 0 , 0 , 0 , 0 , 0
Multiple Barrel Culv=2,6,31,134,0.013,0.5,1,8,3,78,76,3,Culvert #1, 0, 26.378
 9938.00 9938.0010000.0010000.0010062.0010062.00
Culvert Bottom n=0.013
BC Design=,, 0 ,, 0 ,,,,,,

Type RM Length L Ch R = 1 ,9673.649,235.739900,235.739900,235.739900
XS GIS Cut Line= 2
869070.062956586757260.056147532868299.802074365757579.047937327
#Sta/Elev= 30
9569.475 104.8899574.955105.01829585.779102.48769629.073 81.09239639.89778.94442
 9650.72 79.43319737.30979.328119834.72281.975629845.54583.084369878.01683.54259
9921.31183.148669942.95883.935989953.78283.481549964.60581.820489975.429 78.5694
10000.5676.49795 10026.779.5361710040.3784.2868910051.1986.5745110062.0287.52901
10072.8491.2066210105.3193.1333110116.1495.6450410126.9695.7445810170.2599.01967
10202.7298.9904510289.31105.292910310.96106.364310354.26107.088410403.18109.9565
#Mann= 3 , 0 , 0
9569.475  0.0582       09569.475  0.0582       010403.18  0.0582       0
#XS Ineff= 2 , 0
       0 9949.02                       0
Bank Sta=9569.475,10403.18
Exp/Cntr=0.3,0.1

Type RM Length L Ch R = 1 ,9437.909,235.739900,235.739900,235.739900
XS GIS Cut Line= 6
869044.154609037757196.954979328868940.613279596757188.487867528
868827.010608563757184.519629836868736.390848879757186.738130754
868492.198501825757201.446415357868235.655916636757196.204766324
#Sta/Elev= 30
9595.248 95.03259614.46685.91168  9624.582.438869664.63379.026659674.66774.38527
9694.73377.542989704.75176.63616 9734.77  79.3059844.82780.298339924.90784.75697
9944.96684.954559954.99684.319929975.05479.193829985.08474.412059995.11372.61412
10005.1476.5564610025.1875.44333 10035.2 76.757710055.25  84.79910065.2786.15591
10195.3390.1770510225.3394.7836310265.3398.0876310305.3599.6731110315.36100.9198
10325.37104.060110375.41 110.68310385.41113.523510395.42 114.34410404.77 116.669
#Mann= 3 , 0 , 0
9595.248  0.0619       09595.248  0.0619       010404.77  0.0619       0
#XS Ineff= 2 , 0
       09938.751                       0
Bank Sta=9595.248,10404.77
Exp/Cntr=0.3,0.1

Type RM Length L Ch R = 1 ,9202.169,235.739800,235.739800,235.739800
XS GIS Cut Line= 6
869059.034822566757080.265123152 868968.69871002757056.660945741
868889.825147076757034.091156126 868490.66062403756912.382985562
868373.784769665756880.490744771868243.154024951756847.847797153
#Sta/Elev= 30
9575.74198.365719621.25595.42463 9631.5994.424099652.262 91.00069672.95889.40849
9704.16288.820799747.84689.518479777.12288.894119850.12689.799529892.20582.06426
9934.05480.904069954.97874.399249996.82670.9650110007.2671.8396110017.7178.18274
10028.1580.83749 10038.680.6915510059.4978.8884510090.82 78.802610101.2679.85318
10132.5980.1909710159.3982.3649810184.6985.5907710215.79 86.356110226.1588.44383
10257.2591.6357810298.66 93.151510308.9794.8847210339.89 96.023210424.26106.6583
#Mann= 3 , 0 , 0
9575.741  0.0421       09575.741  0.0421       010424.26  0.0421       0
#XS Ineff= 2 , 0
       09841.043                       0
Bank Sta=9575.741,10424.26
Exp/Cntr=0.3,0.1

Type RM Length L Ch R = 1 ,8966.429,235.739900,235.739900,235.739900
XS GIS Cut Line= 6
868999.670502372756927.910395123868844.982197327756823.699964544
868749.320261377756735.809167876868678.694896225756684.215817156
868556.976488737 756616.04813837868421.531903586756556.858833172
#Sta/Elev= 30
9733.45992.096659774.848 88.95969799.10581.579679810.97980.273849822.983 80.8625
9834.83278.75557 9846.6877.650619858.529  77.9369870.37876.956289907.59279.01319
9920.04378.144679946.27977.778169964.33278.902369973.01976.83882 9978.6873.47422
9987.04870.43682    999969.5776210021.2472.7480410036.2473.3335510051.3572.66442
10067.66 74.112210093.4881.4813810117.7976.72225 10129.976.7380410165.25  79.335
10176.9579.1079110301.2882.7992710334.2984.5579610367.1385.0310610424.9488.37139
#Mann= 3 , 0 , 0
9733.459  0.0513       09733.459  0.0513       010424.94  0.0513       0
#XS Ineff= 2 , 0
       09940.328                       0
Bank Sta=9733.459,10424.94
Exp/Cntr=0.3,0.1

Type RM Length L Ch R = 1 ,8730.689,235.739900,235.739900,235.739900
XS GIS Cut Line= 6
869149.271930223756704.613963036869029.728649641756646.975926335
868955.093186276756604.365095916868860.658452192 756538.33111237
868789.865321277756499.924345385868522.503905681756389.405667972
#Sta/Elev= 30
9726.40586.196159742.13785.677789764.18383.786699786.229 82.71159797.29780.81323
9808.485 80.60669853.23676.737389876.09376.948539887.60876.380869933.668 76.3351
 9945.19 74.0408 9961.3771.72293 9981.8567.3026510006.3267.49422 10018.566.96829
10030.6769.2837310042.8573.0917110048.6274.1395110066.8577.0451710089.9679.91673
10129.7679.9434410140.8879.3353610157.1477.2957510179.0376.8353210200.9278.89059
10226.8379.1464410266.5880.7944110277.3281.7422210320.2582.7544410430.2688.44873
#Mann= 3 , 0 , 0
9726.405    0.04       09726.405    0.04       010430.26    0.04       0
#XS Ineff= 2 , 0
       09918.055                       0
Bank Sta=9726.405,10430.26
Exp/Cntr=0.3,0.1

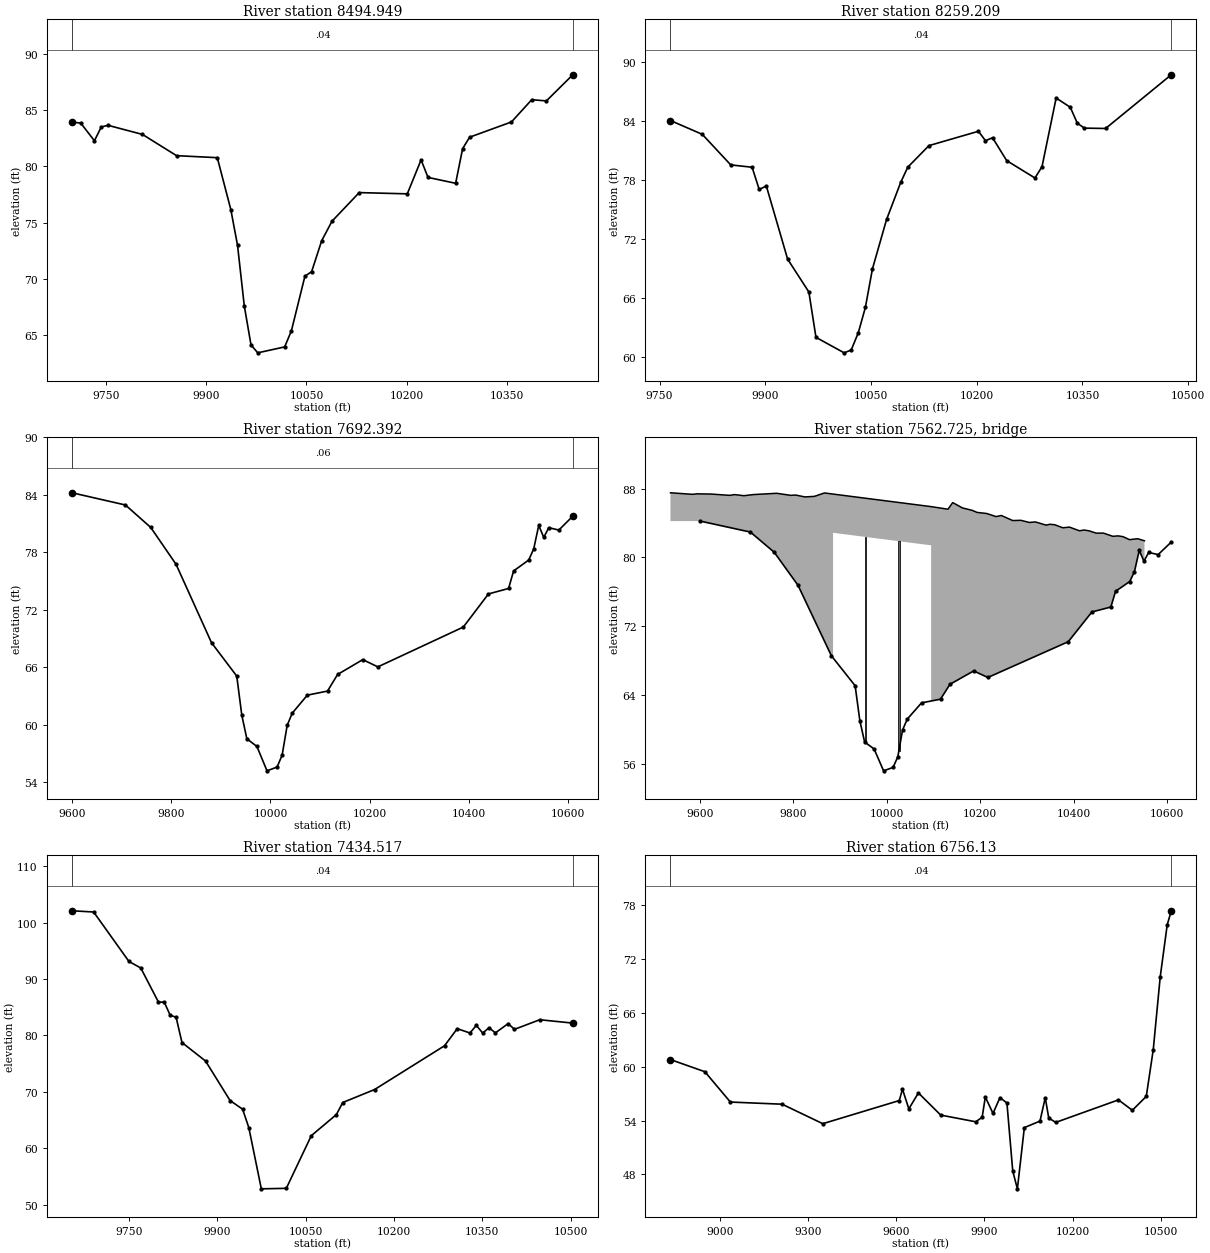
Type RM Length L Ch R = 1 ,8494.949,235.739900,235.739900,235.739900
XS GIS Cut Line= 6
869277.670884027 756409.08405441 869150.49597509756379.358345077
869054.515086876756362.317886277868910.135154793756343.696154759
868829.671019195756327.810539105868547.127154503756247.272257051
#Sta/Elev= 30
9699.12583.941539712.13783.861599732.676 82.28639742.94683.517269753.21683.65702
9804.563 82.85059855.62280.960839916.56180.78258  9936.876.171779946.87972.98497
9956.958 67.60779967.03764.133429977.11763.4288310017.4463.9569510027.5365.39782
 10047.7 70.238910057.7970.6527210072.7973.3923110088.2175.1294710128.99 77.6775
10200.9577.5664510221.6180.5872810231.9479.0276110273.3178.5054810283.7581.57977
 10294.282.6035810356.8783.9587610387.2985.94087 10409.185.8278310448.6688.15397
#Mann= 3 , 0 , 0
9699.125    0.04       09699.125    0.04       010448.66    0.04       0
#XS Ineff= 2 , 0
       0                               0
Bank Sta=9699.125,10448.66
Exp/Cntr=0.3,0.1

Type RM Length L Ch R = 1 ,8259.209,566.817700,566.817700,566.817700
XS GIS Cut Line= 6
 869249.61007386756147.933136794869104.444760956756127.204259484
869045.565423957756121.185879415869001.710335174756120.162197978
 868971.43786092756117.719376554868542.086931255   756088.142419
#Sta/Elev= 30
9765.506 84.03749810.579 82.63359850.99179.521559881.28779.282489891.38677.01888
9901.48577.373829931.69169.925849961.84766.578889971.89661.9635810011.9160.38669
10021.9360.6758110031.9762.43611   1004265.0092410052.0368.9385710072.07 73.9662
10092.1277.7396710102.1479.2898810132.2281.4852710202.3882.94475 10212.481.98526
10222.4382.2858210242.4879.9551710282.5778.1876710292.5979.3403610312.64 86.3334
10332.6985.3871710342.7183.7610510352.74 83.264710382.8183.2291610475.9488.69624
#Mann= 3 , 0 , 0
9765.506    0.04       09765.506    0.04       010475.94    0.04       0
#XS Ineff= 2 , 0
       0                10153.94       0
Bank Sta=9765.506,10475.94
Exp/Cntr=0.3,0.1

Type RM Length L Ch R = 1 ,7692.392,257.874900,257.874900,257.874900
XS GIS Cut Line= 4
869269.533028951755990.494778477869209.464870918755690.048285645
869164.109251656755432.307805237869094.586522843754997.289428567
#Sta/Elev= 30
9600.36684.227399707.94882.951699758.93880.606629809.92776.758059881.31368.57382
9932.19165.085749942.34560.998769952.49958.541669972.80657.737279993.11355.19339
10013.4255.5904610023.5756.8316210033.7359.9421410043.88 61.214310074.3463.09633
10114.9663.5222310135.2665.2552610185.9966.8063510216.3766.0484210388.5270.20687
10439.1673.6653110479.6774.2358510489.7976.0659810520.1777.20464 10530.3 78.3673
10540.4380.8189810550.5579.5690110560.6880.5822110580.9480.33371   1060981.78731
#Mann= 3 , 0 , 0
9600.366    0.06       09600.366    0.06       0   10609    0.06       0
#XS Ineff= 2 , 0
       0                10139.93       0
Bank Sta=9600.366,10609
Exp/Cntr=0.3,0.1

Type RM Length L Ch R = 3 ,7562.725,,,
BEGIN DESCRIPTION:
END DESCRIPTION:
Bridge Culvert--1,0,-1,-1, 0
Deck Dist Width WeirC Skew NumUp NumDn MinLoCord MaxHiCord MaxSubmerge Is_Ogee
68.937450,120.000000,2.6,0, 46, 46, , , 0.95, 0, 0,0,,
 9536.86 9583.95 9593.96 9624.00 9664.05 9674.06 9694.08 9714.11 9764.24 9794.41
 9804.47 9824.59 9844.71 9866.54 9884.92 9884.9210094.9210094.9210130.8710141.11
10161.8710182.7110193.1210213.9610233.8610245.2010269.5910286.8710305.3210318.12
10341.0510349.3710359.7810376.7810391.0310412.5110422.2810432.7010448.2410463.95
10483.9710495.1910505.6110519.7010536.8610551.64
   87.52   87.34   87.40   87.37   87.22   87.31   87.18   87.31   87.46   87.22
   87.26   87.04   87.10   87.50   87.37   87.37   85.91   85.91   85.61   86.38
   85.76   85.48   85.24   85.11   84.75   84.88   84.29   84.32   84.07   84.13
   83.76   83.86   83.80   83.45   83.53   83.10   83.19   83.10   82.83   82.83
   82.46   82.51   82.42   82.07   82.18   81.94
 -912.48 -912.66 -912.60 -912.63 -912.78 -912.69 -912.82 -912.69 -912.54 -912.78
 -912.74 -912.96 -912.90 -912.50 -912.63   82.87   81.41 -914.09 -914.39 -913.62
 -914.24 -914.52 -914.76 -914.89 -915.25 -915.12 -915.71 -915.68 -915.93 -915.87
 -916.24 -916.14 -916.20 -916.55 -916.47 -916.90 -916.81 -916.90 -917.17 -917.17
 -917.54 -917.49 -917.58 -917.93 -917.82 -918.06
 9536.86 9583.95 9593.96 9624.00 9664.05 9674.06 9694.08 9714.11 9764.24 9794.41
 9804.47 9824.59 9844.71 9866.54 9901.01 9901.0110111.0110111.0110130.8710141.11
10161.8710182.7110193.1210213.9610233.8610245.2010269.5910286.8710305.3210318.12
10341.0510349.3710359.7810376.7810391.0310412.5110422.2810432.7010448.2410463.95
10483.9710495.1910505.6110519.7010536.8610551.64
   87.52   87.34   87.40   87.37   87.22   87.31   87.18   87.31   87.46   87.22
   87.26   87.04   87.10   87.50   87.26   87.26   85.80   85.80   85.61   86.38
   85.76   85.48   85.24   85.11   84.75   84.88   84.29   84.32   84.07   84.13
   83.76   83.86   83.80   83.45   83.53   83.10   83.19   83.10   82.83   82.83
   82.46   82.51   82.42   82.07   82.18   81.94
 -912.48 -912.66 -912.60 -912.63 -912.78 -912.69 -912.82 -912.69 -912.54 -912.78
 -912.74 -912.96 -912.90 -912.50 -912.74   82.76   81.30 -914.20 -914.39 -913.62
 -914.24 -914.52 -914.76 -914.89 -915.25 -915.12 -915.71 -915.68 -915.93 -915.87
 -916.24 -916.14 -916.20 -916.55 -916.47 -916.90 -916.81 -916.90 -917.17 -917.17
 -917.54 -917.49 -917.58 -917.93 -917.82 -918.06
Pier Skew, UpSta & Num, DnSta & Num=  ,9954.26, 2 ,9970.35, 2 , 0 , 0 , 0 ,,
    4.00    4.00
 -913.11   86.89
    4.00    4.00
 -913.22   86.78
Pier Skew, UpSta & Num, DnSta & Num=  ,10025.59, 2 ,10041.68, 2 , 0 , 0 , 0 ,,
    4.00    4.00
 -913.61   86.39
    4.00    4.00
 -913.72   86.28
BR Coef=-1 , 0 , 0 ,, 0 ,,,0.8,0,1,0,
WSPro=,,,, 1 ,,,, 0 ,,,, 0 ,,,,-1 ,-1 ,-1 , 0 , 0 , 0 , 0 , 0
BC Design=,, 0 ,, 0 ,,,,,,

Type RM Length L Ch R = 1 ,7434.517,678.386900,678.386900,678.386900
XS GIS Cut Line= 4
869420.923899312755761.716831327869416.358465173755523.391401841
 869350.13366484755336.130145474869193.775543021754953.322578483
#Sta/Elev= 30
9653.176102.11219689.899 101.896 9749.9193.117779769.91491.973169799.91985.92945
9809.92185.888929819.92383.581849829.92583.240359839.92778.745659879.93475.47001
9921.65968.452239942.87366.92765 9953.4863.645699974.69452.7996610017.1252.89022
10059.5562.2253210102.1965.97114   1011368.1098510167.0170.4073310285.8378.17344
10307.4381.2023910329.0480.4395210339.8481.7867910350.6480.4342210361.4481.36574
10372.2480.4604110393.8582.0986110404.65 81.084210447.5582.7890510503.6882.19253
#Mann= 3 , 0 , 0
9653.176    0.04       09653.176    0.04       010503.68    0.04       0
#XS Ineff= 2 , 0
       0                10122.08       0
Bank Sta=9653.176,10503.68
Exp/Cntr=0.3,0.1

Type RM Length L Ch R = 1 , 6756.13,531.332600,531.332600,531.332600
XS GIS Cut Line= 3
870003.027648775755812.892291098869575.595637081754801.606775133
869063.323918036754474.207693626
#Sta/Elev= 30
8830.42260.800598947.55559.447029034.40856.064989210.64755.826289349.24753.65289
9609.80456.233489620.66157.506959642.37455.307179674.94357.085149750.93954.61253
9870.36153.864919892.07454.36853 9902.93 56.63039929.03454.79847 9952.7756.56174
9976.50655.963289996.30448.3787810012.1146.3885310035.8553.2159510089.1553.94224
10107.0556.5539610118.9254.2915610142.6653.7958710356.2856.3070810403.7555.15069
10451.2256.6971810474.9661.9052210498.6970.0272110522.4375.8110910536.28 77.3934
#Mann= 3 , 0 , 0
8830.422    0.04       08830.422    0.04       010536.28    0.04       0
#XS Ineff= 2 , 0
       09918.263        10219.73       0
Bank Sta=8830.422,10536.28
Exp/Cntr=0.3,0.1