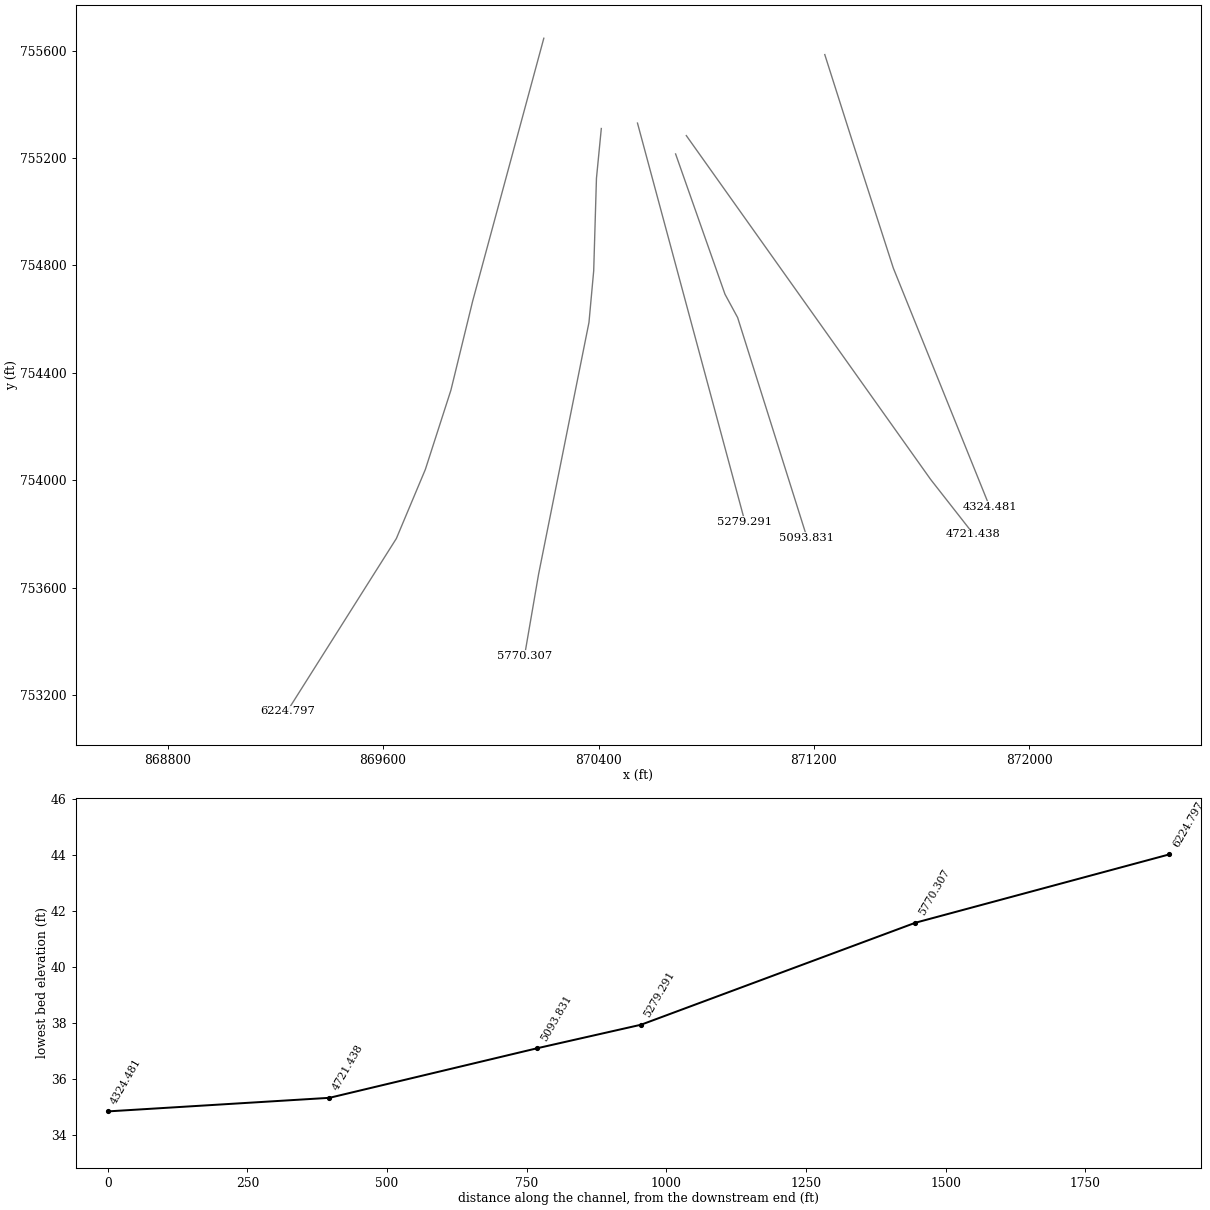
HEC-RAS study 9116_ras.prj: 9116

--- 9116_ras.g01 (geometry) --- (continued)

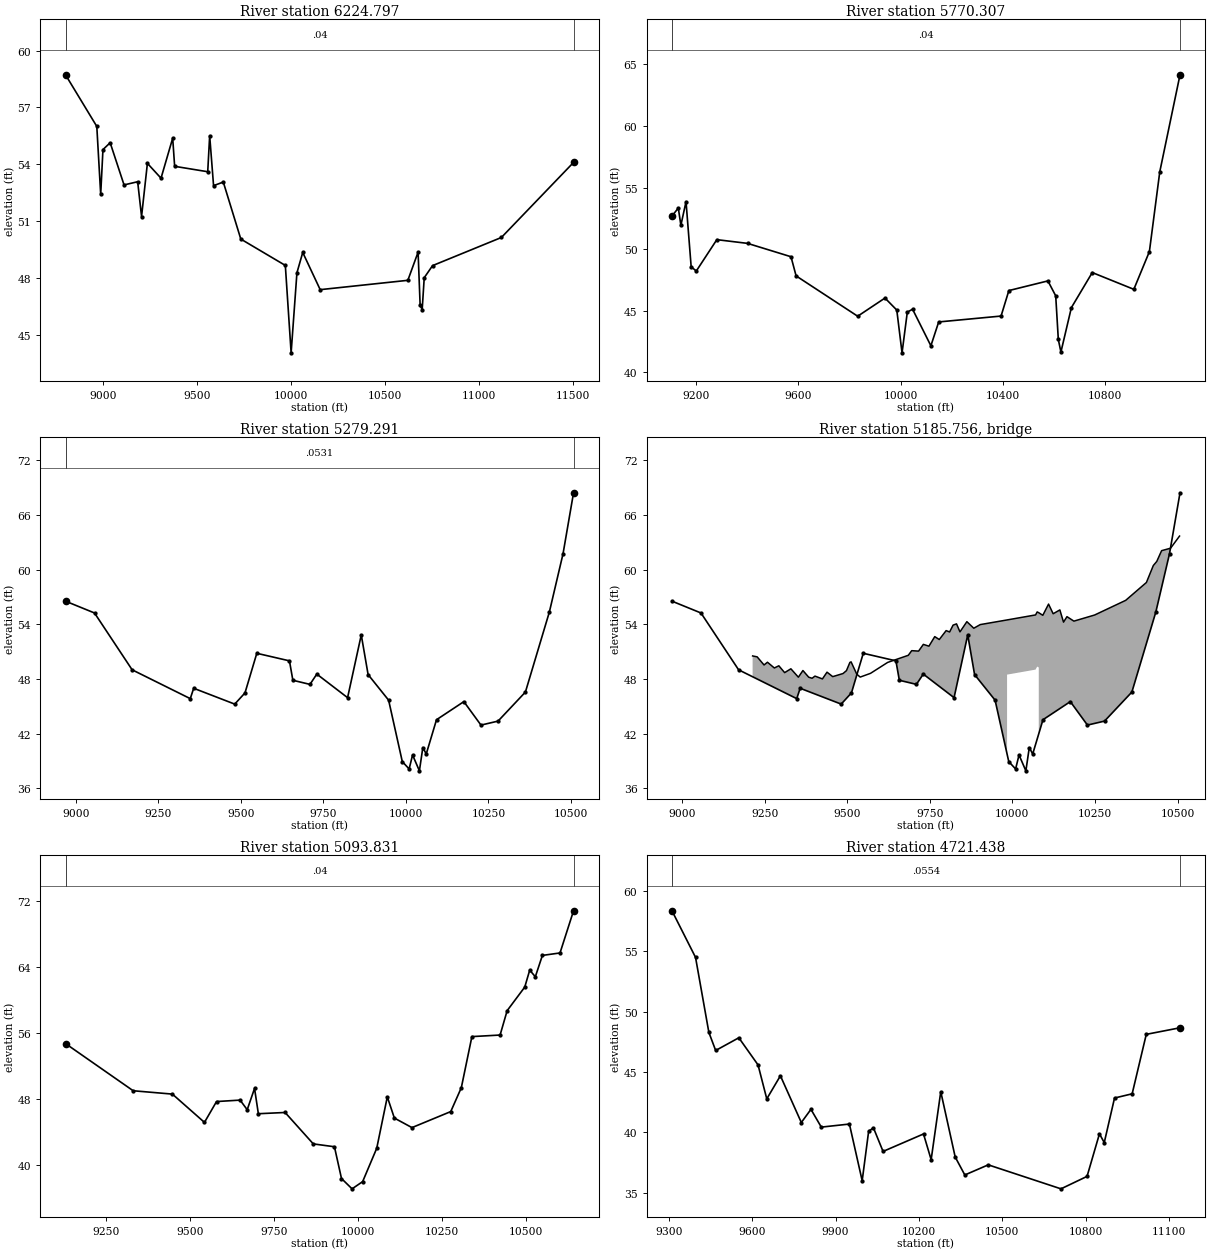
Type RM Length L Ch R = 1 ,6224.797,454.490200,454.490200,454.490200
XS GIS Cut Line= 6
 870196.93902896755645.811769938869932.691059349754666.798651922
869851.952173382 754335.27980914 869757.04458525754040.055236685
869649.419730758753782.950216223869244.420228169753140.075510971
#Sta/Elev= 30
8798.74158.721838965.30855.993918986.02452.400538998.057 54.76939036.43255.13118
9110.31852.903149182.823 53.07069203.53951.234329234.61254.042389307.11753.25799
9369.26555.373479379.62353.885749555.70653.599469566.06455.50518 9586.7852.86361
9638.569 53.0543 9731.7950.041699968.791 48.6497 9999.6244.03122 10030.548.26022
10061.4549.33441 10154.347.3694110620.8947.8625710675.39 49.350810686.2946.54228
10697.18 46.320110708.08 48.000710752.4148.63871 11118.850.1261311502.8354.09103
#Mann= 3 , 0 , 0
8798.741    0.04       08798.741    0.04       011502.83    0.04       0
#XS Ineff= 2 , 0
       0 9891.48        10802.35       0
Bank Sta=8798.741,11502.83
Exp/Cntr=0.3,0.1

Type RM Length L Ch R = 1 ,5770.307,491.016400,491.016400,491.016400
XS GIS Cut Line= 6
870410.396889743755309.643775873870392.371078636755124.144863555
870382.155591937 754780.03820466870364.561405195754587.318375142
 870177.46540529753649.916316069870125.441498061753346.924361923
#Sta/Elev= 30
9105.47452.685329130.27553.336179140.33951.937499160.46653.857539180.59448.56029
9200.72148.226779281.00250.770219401.11450.468259571.17149.383879591.17747.82881
9832.08744.556229938.86846.031199985.072 45.056410005.6441.5847710026.2344.88688
10046.8245.1256610118.4842.1562210149.0644.0922610393.0844.5697310423.5846.63881
10576.33 47.422210606.8946.2106610617.0842.6685710627.2841.6504310668.1745.25275
10749.9448.1005310912.5546.7390310973.4349.8009611014.0256.2767311093.2364.15051
#Mann= 3 , 0 , 0
9105.474    0.04       09105.474    0.04       011093.23    0.04       0
#XS Ineff= 2 , 0
       09717.883        10515.96       0
Bank Sta=9105.474,11093.23
Exp/Cntr=0.3,0.1

Type RM Length L Ch R = 1 ,5279.291,185.459600,185.459600,185.459600
XS GIS Cut Line= 2
870544.719833427 755329.82423837870943.838958517753844.271809719
#Sta/Elev= 30
8969.30156.549429057.13355.252469171.03449.018969347.06245.855239357.41746.99224
9481.67245.255239512.73646.485529548.49150.830799647.34650.000799657.70147.86981
9709.47447.420259730.18348.548229823.37545.961359864.79352.848239885.503 48.4941
 9947.63  45.6869989.04938.9444810009.7638.1403710020.1139.6749710040.8237.93436
10051.1840.4890410061.5339.78583 10092.643.5410710175.4345.5281810227.2142.95342
10278.9843.3902610361.8246.57988 10434.355.3580910475.7261.7522610507.5368.44064
#Mann= 3 , 0 , 0
8969.301  0.0531       08969.301  0.0531       010507.53  0.0531       0
#XS Ineff= 2 , 0
       09920.133        10081.85       0
Bank Sta=8969.301,10507.53
Exp/Cntr=0.3,0.1

Type RM Length L Ch R = 3 ,5185.756,,,
BEGIN DESCRIPTION:
END DESCRIPTION:
Bridge Culvert--1,0,-1,-1, 0
Deck Dist Width WeirC Skew NumUp NumDn MinLoCord MaxHiCord MaxSubmerge Is_Ogee
49.729800,86.000000,2.6,0, 60, 60, , , 0.95, 0, 0,0,,
 9213.48 9227.23 9248.03 9258.43 9279.23 9292.87 9310.42 9329.33 9352.02 9365.79
 9383.21 9393.61 9402.26 9424.81 9438.72 9456.01 9487.20 9497.60 9508.00 9511.65
 9528.80 9539.20 9570.39 9622.38 9684.78 9695.18 9715.97 9730.42 9747.25 9764.93
 9778.60 9799.39 9809.95 9820.40 9830.84 9841.29 9862.19 9883.09 9902.65 9983.88
 9983.8810070.1510075.0610079.8810079.8810092.0910109.5210123.4410143.7610154.81
10165.2710186.1810248.9210343.0310405.7710426.6810437.1310451.7610478.9610506.07
   50.54   50.44   49.55   49.85   49.22   49.46   48.71   49.13   48.21   48.94
   48.21   48.09   48.33   48.02   48.76   48.27   48.61   48.93   49.83   49.89
   48.54   48.22   48.63   49.83   50.61   51.12   51.07   51.81   51.61   52.66
   52.34   53.32   53.17   53.92   54.06   53.18   54.30   53.58   53.98   54.49
   54.49   55.04   55.37   55.28   55.28   55.00   56.23   55.17   55.59   54.25
   54.85   54.36   55.03   56.64   58.60   60.46   60.91   62.09   62.36   63.69
 -949.46 -949.56 -950.45 -950.15 -950.78 -950.54 -951.29 -950.87 -951.79 -951.06
 -951.79 -951.91 -951.67 -951.98 -951.24 -951.73 -951.39 -951.07 -950.17 -950.11
 -951.46 -951.78 -951.37 -950.17 -949.39 -948.88 -948.93 -948.19 -948.39 -947.34
 -947.66 -946.68 -946.83 -946.08 -945.94 -946.82 -945.70 -946.42 -946.02 -945.51
   48.49   49.04   49.37   49.28 -944.72 -945.00 -943.77 -944.83 -944.41 -945.75
 -945.15 -945.64 -944.97 -943.36 -941.40 -939.54 -939.09 -937.91 -937.64 -936.31
 9213.48 9227.23 9248.03 9258.43 9279.23 9292.87 9310.42 9329.33 9352.02 9365.79
 9383.21 9393.61 9402.26 9424.81 9438.72 9456.01 9487.20 9497.60 9508.00 9511.65
 9528.80 9539.20 9570.39 9622.38 9684.78 9695.18 9715.97 9730.42 9747.25 9764.93
 9778.60 9799.39 9809.95 9820.40 9830.84 9841.29 9862.19 9883.09 9902.65 9951.15
 9951.1510047.1510047.1510070.1510075.0610092.0910109.5210123.4410143.7610154.81
10165.2710186.1810248.9210343.0310405.7710426.6810437.1310451.7610478.9610506.07
   50.54   50.44   49.55   49.85   49.22   49.46   48.71   49.13   48.21   48.94
   48.21   48.09   48.33   48.02   48.76   48.27   48.61   48.93   49.83   49.89
   48.54   48.22   48.63   49.83   50.61   51.12   51.07   51.81   51.61   52.66
   52.34   53.32   53.17   53.92   54.06   53.18   54.30   53.58   53.98   54.29
   54.29   54.89   54.89   55.04   55.37   55.00   56.23   55.17   55.59   54.25
   54.85   54.36   55.03   56.64   58.60   60.46   60.91   62.09   62.36   63.69
 -949.46 -949.56 -950.45 -950.15 -950.78 -950.54 -951.29 -950.87 -951.79 -951.06
 -951.79 -951.91 -951.67 -951.98 -951.24 -951.73 -951.39 -951.07 -950.17 -950.11
 -951.46 -951.78 -951.37 -950.17 -949.39 -948.88 -948.93 -948.19 -948.39 -947.34
 -947.66 -946.68 -946.83 -946.08 -945.94 -946.82 -945.70 -946.42 -946.02 -945.71
   48.29   48.89 -945.11 -944.96 -944.63 -945.00 -943.77 -944.83 -944.41 -945.75
 -945.15 -945.64 -944.97 -943.36 -941.40 -939.54 -939.09 -937.91 -937.64 -936.31
BR Coef=-1 , 0 , 0 ,, 0 ,,,0.8,0,1,0,
WSPro=,,,, 1 ,,,, 0 ,,,, 0 ,,,,-1 ,-1 ,-1 , 0 , 0 , 0 , 0 , 0
BC Design=,, 0 ,, 0 ,,,,,,

Type RM Length L Ch R = 1 ,5093.831,372.393200,372.393200,372.393200
XS GIS Cut Line= 4
870686.246895506755214.934881876870869.586522118754692.578280085
870916.555033597754605.725772009871174.103856659753786.598741646
#Sta/Elev= 30
 9130.6854.686819331.97448.972629448.55348.567979543.93645.141879579.84247.66529
9649.91647.840189671.11246.675579692.89349.254879704.26146.191119783.77746.34118
9867.63842.536599930.53442.190999951.49938.343769982.94737.09432 10014.437.96769
10056.3342.0079910087.7748.2345910108.74 45.665510161.1544.5101710276.4646.45103
10307.9149.3436510339.3655.5303810423.2255.7200810444.1858.67126 10496.661.53102
10511.3163.5819910528.0462.7785810549.0165.3637510601.4265.6603410641.6870.76844
#Mann= 3 , 0 , 0
 9130.68    0.04       0 9130.68    0.04       010641.68    0.04       0
#XS Ineff= 2 , 0
       09904.324        10088.43       0
Bank Sta=9130.68,10641.68
Exp/Cntr=0.3,0.1

Type RM Length L Ch R = 1 ,4721.438,396.957200,396.957200,396.957200
XS GIS Cut Line= 3
870725.985079931755283.253693725 871633.25010839754002.872106049
871792.203197693753799.344606919
#Sta/Elev= 30
9311.73858.347979396.51654.489359444.414 48.27749468.92646.776019552.18347.82908
9621.369 45.58159652.76642.76823 9701.7944.681939777.03640.810139811.62941.90182
9848.86240.429829949.999 40.68329995.93535.9877710019.1840.0877810036.4840.36998
10071.07 38.415210216.54  39.86310244.0437.7325810278.6343.3630510330.5237.95419
10365.1136.4651910449.4137.3045410711.04 35.317310804.8336.3494710849.4139.87318
10866.7139.1486410903.6542.8392110967.09 43.188411017.8548.1130611139.2248.65732
#Mann= 3 , 0 , 0
9311.738  0.0554       09311.738  0.0554       011139.22  0.0554       0
#XS Ineff= 2 , 0
       0 9897.02        10279.55       0
Bank Sta=9311.738,11139.22
Exp/Cntr=0.3,0.1

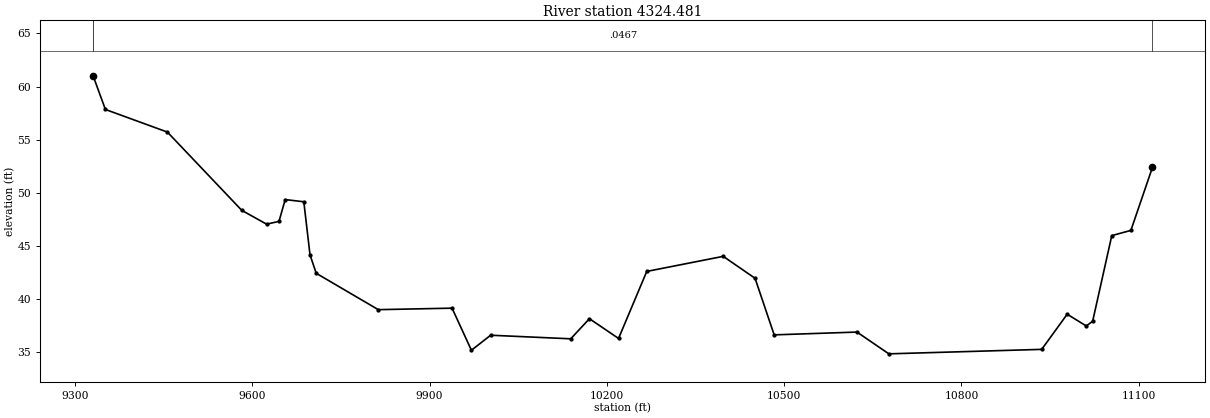
Type RM Length L Ch R = 1 ,4324.481,0.000000,0.000000,0.000000
XS GIS Cut Line= 4
871240.153982834755584.907288369871340.262419527755269.412161107
871494.574468021754790.028237325871852.490209633753901.149164109
#Sta/Elev= 30
9330.44761.014829351.33357.841449456.24655.712369582.14248.340139624.10747.04381
 9645.0947.303029655.58249.35579 9687.0949.150769697.59544.14963  9708.142.41535
9813.15338.991329937.99139.132049970.73335.1659910003.2636.5831210138.82 36.2463
10170.4738.1399910219.74 36.279910267.4942.5921810396.8644.0109510450.7641.94582
 10483.136.6176210623.2436.8810910677.1434.8307610935.8735.2516210978.9938.56253
11011.3337.4547311022.1137.9034411054.4545.9643411086.7946.4533711123.2852.39202
#Mann= 3 , 0 , 0
9330.447  0.0467       09330.447  0.0467       011123.28  0.0467       0
#XS Ineff= 2 , 0
       09859.601         10269.6       0
Bank Sta=9330.447,11123.28
Exp/Cntr=0.3,0.1